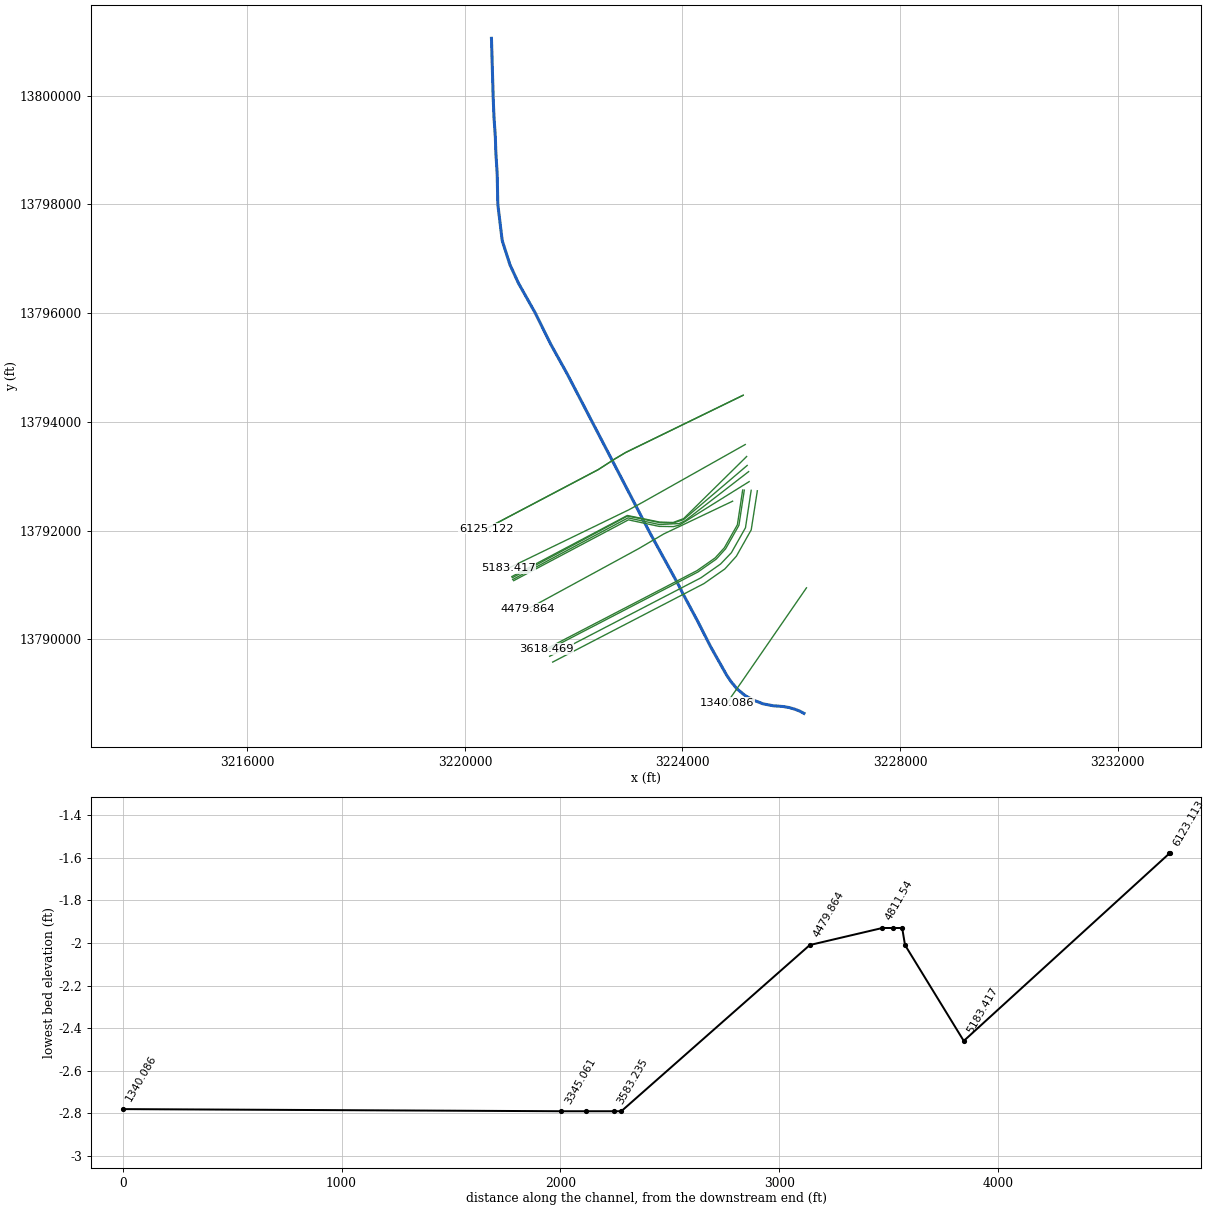
--- A104_13_00.prj (project) ---

Proj Title=A104-13-00
Current Plan=p02
Default Exp/Contr=.3,.1
English Units
Geom File=g01
Geom File=g02
Flow File=f02
Flow File=f01
Plan File=p01
Plan File=p02
Y Axis Title=Elevation
X Axis Title(PF)=Main Channel Distance
X Axis Title(XS)=Station
BEGIN DESCRIPTION:
Clear Creek Basin
Taylor Bayou Tributary 3.36
A104-13-00
Flood Hazard Model
10, 2, 1 & 0.2% Events
Filename: A104_13_00.prj
Prepared by: Perry Vaught	Date: 4-20-04
Reviewed by: __________	Date:
Status (FINAL)
TROPICAL STORM ALLISON RECOVERY PROJECT
END DESCRIPTION:
DSS Export Rating Curves= 0
DSS Export Rating Curve Sorted= 0
DSS Export Volume Flow Curves= 0
DXF OffsetX= 0
DXF OffsetY= 0
DXF ScaleX= 1
DXF ScaleY= 10

--- A104_13_00.p02 (plan) ---

Plan Title=Floodway
Version=Version 3.0.1  Mar 2001
Short Identifier=Floodway0607
Geom File=g02
Flow File=f02
Subcritical Flow
K Sum by GR= 0
Std Step Tol= 0.01
Critical Tol= 0.01
Num of Std Step Trials= 20
Max Error Tol= 0.3
Flow Tol Ratio= 0.001
Split Flow NTrial= 30
Split Flow Tol= 0.02
Split Flow Ratio= 0.02
Log Output Level= 0
Friction Slope Method= 0
Unsteady Friction Slope Method= 2
Secant Critical Depth
Global Vel Dist= 0 , 0 , 0
Global Log Level= 0
CheckData=True
Encroach Param=-1 ,0,0, 2
Encroach River=A104-13-00
Encroach Reach=A104-13-00_0013
Encroach Node=6125.122
       1 4935.61 5064.39
Encroach Node=6124
       1 4935.61 5064.39
Encroach Node=6123.113
       1 4935.61 5064.39
Encroach Node=5183.417
       1 4933.14 5056.86
Encroach Node=4914.941
       1    4900 5068.74
Encroach Node=4902.016
       1 4906.85 5093.15
Encroach Node=4880
       1 4906.85 5093.15
Encroach Node=4858.328
       1 4906.85 5093.15
Encroach Node=4811.54
       1 4906.85 5093.15
Encroach Node=4479.864
       1 4936.26 5073.74
Encroach Node=3618.469
       1 4943.89 5056.11
Encroach Node=3583.235
       1 4943.89 5056.11
Encroach Node=3520
       1 4943.89 5056.11
Encroach Node=3457.532
       1 4943.89 5056.11
Encroach Node=3345.061
       1 4943.89 5056.11
Encroach Node=1340.086
       1    4350    5063
Computation Interval=1HOUR
Output Interval=1HOUR
Run HTab= 0
Run UNet= 0
Run PostProcess= 0
UNET Theta= 1
UNET ZTol= 0.02
UNET ZSATol= 0.1
UNET MxIter= 20
UNET MaxInSteps= 20
UNET DtIC= 0
UNET DtMin= 0
UNET MaxCRTS= 20
UNET WFStab= 2
UNET SFStab= 1
UNET WFX= 1
UNET SFX= 1
UNET Convert EG Bridges=-1
UNET Use Existing IB Tables=-1
Instantaneous Interval=1HOUR
Write IC File= 0
IC Time=0
Write Velocity= 0
Write Detailed= 0

--- A104_13_00.p01 (plan) ---

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Plan Title=FEMA Effective June 2007
Short Identifier=FEMAeff0607
Geom File=g01
Flow File=f01
Std Step Tol= 0.003
Critical Tol= 0.003
Max Error Tol= 0.1

--- A104_13_00.f02 (steady flow) ---

Flow Title=Floodway
Version=Version 3.0.1  Mar 2001
Number of Profiles= 2
Profile Names=1PCT_100yr, 1PCTFloodway_100yrFW
River Rch & RM=A104-13-00,A104-13-00_0013      ,6125.122
    2328    2328
River Rch & RM=A104-13-00,A104-13-00_0013      ,5183.417
    2395    2395
River Rch & RM=A104-13-00,A104-13-00_0013      ,4479.864
    2479    2479
River Rch & RM=A104-13-00,A104-13-00_0013      ,3618.469
    2506    2506
River Rch & RM=A104-13-00,A104-13-00_0013      ,3345.061
    2617    2617
Boundary for River Rch & Prof#=A104-13-00,A104-13-00_0013      , 1
Up Type= 0
Dn Type= 3
Dn Slope=.0001
DSS Import GetInterval= 0
DSS Import GetPeak= 0
DSS Import FillOption= 0

--- A104_13_00.f01 (steady flow) ---

Flow Title=FEMA Effective June 2007
Version=Version 3.0.1  Mar 2001
Number of Profiles= 4
Profile Names=10PCT_10yr, 2PCT_50yr, 1PCT_100yr, 0.2PCT_500yr
River Rch & RM=A104-13-00,A104-13-00_0013      ,6125.122
    1369    2000    2328    3277
River Rch & RM=A104-13-00,A104-13-00_0013      ,5183.417
    1409    2057    2395    3371
River Rch & RM=A104-13-00,A104-13-00_0013      ,4479.864
    1458    2130    2479    3490
River Rch & RM=A104-13-00,A104-13-00_0013      ,3618.469
    1474    2153    2506    3528
River Rch & RM=A104-13-00,A104-13-00_0013      ,3345.061
    1539    2248    2617    3683
Boundary for River Rch & Prof#=A104-13-00,A104-13-00_0013      , 1
Up Type= 0
Dn Type= 3
Dn Slope=.0001
Boundary for River Rch & Prof#=A104-13-00,A104-13-00_0013      , 2
Up Type= 0
Dn Type= 3
Dn Slope=.0001
Boundary for River Rch & Prof#=A104-13-00,A104-13-00_0013      , 3
Up Type= 0
Dn Type= 3
Dn Slope=.0001
Boundary for River Rch & Prof#=A104-13-00,A104-13-00_0013      , 4
Up Type= 0
Dn Type= 3
Dn Slope=.0001
DSS Import GetInterval= 0
DSS Import GetPeak= 0
DSS Import FillOption= 0

--- A104_13_00.g02 (geometry) ---

Geom Title=A104-13-00 June 2007 (Floodway)
Version=Version 3.0.1  Mar 2001

River Reach=A104-13-00,A104-13-00_0013
Reach XY= 30
        3220488.       13801052.      3220519.25       13799974.
        3220534.       13799608.       3220559.5       13799234.
       3220568.5       13798954.       3220593.5       13798550.
      3220604.75       13798002.      3220685.25       13797334.
      3220827.75       13796890.       3220983.5       13796552.
        3221293.       13796002.      3221578.25       13795426.
      3221885.75       13794872.       3223401.5       13791959.
       3223935.5       13790987.        3223982.       13790890.
       3224275.5       13790342.      3224517.25       13789867.
      3224811.75       13789344.      3224896.25       13789219.
      3225002.25       13789091.       3225154.5    13788964.999
      3225300.25       13788886.        3225479.       13788816.
      3225667.75       13788780.      3225849.75       13788766.
       3225961.5       13788747.      3226061.75       13788718.
       3226155.5       13788682.      3226233.75       13788640.

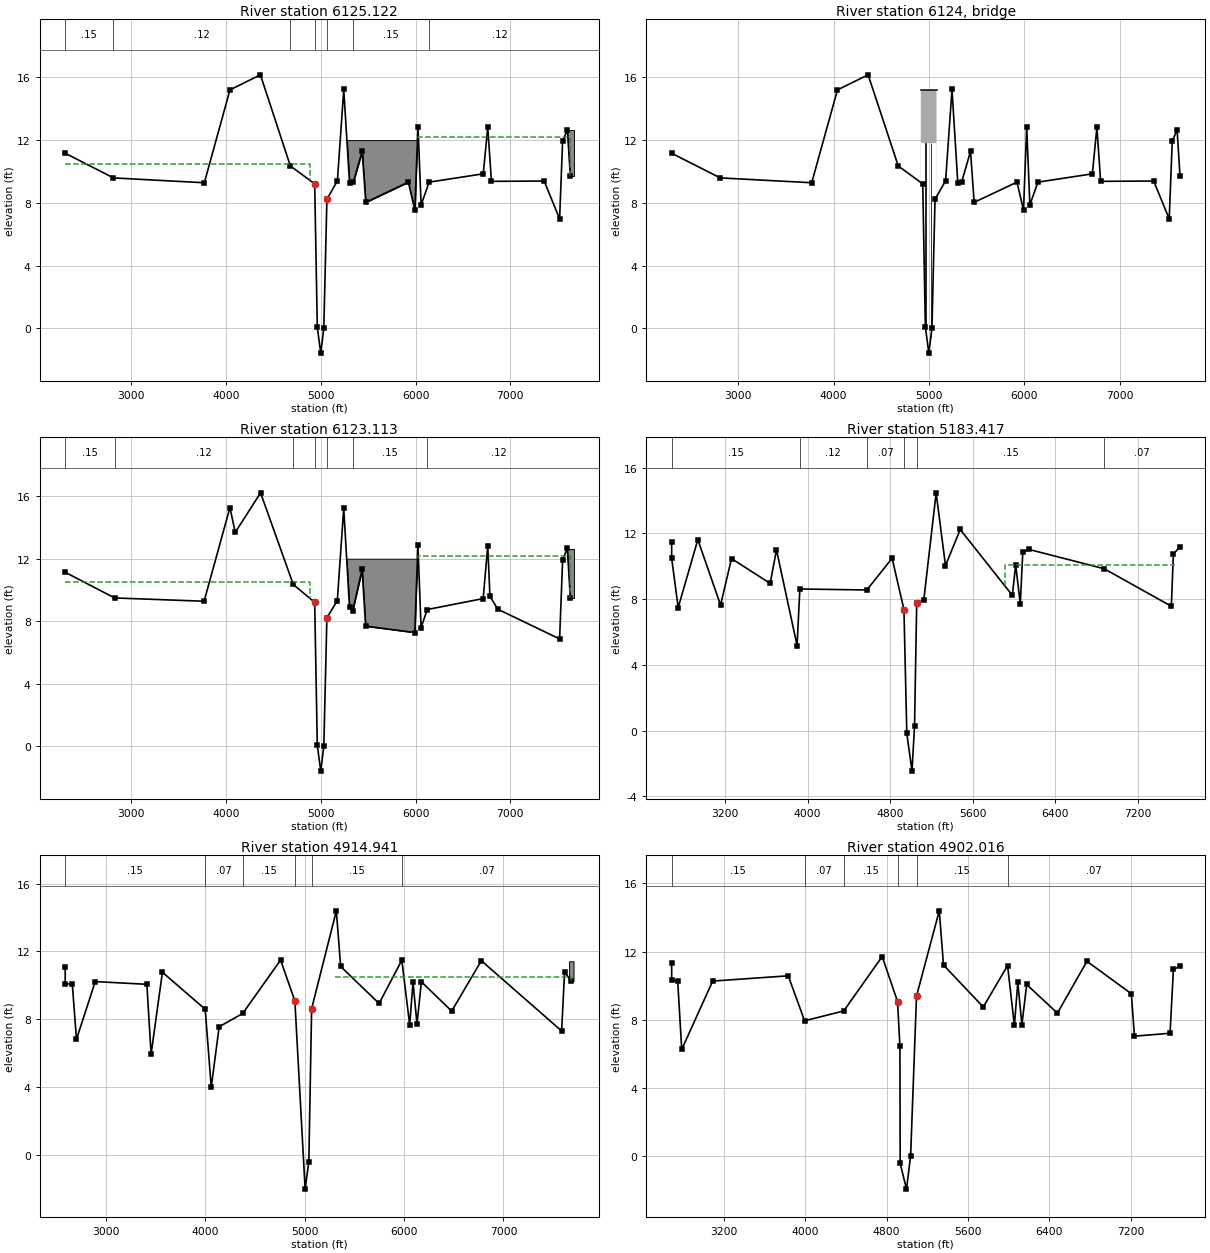
Type RM Length L Ch R = 1 ,6125.122,2,2.01,2.01
XS GIS Cut Line= 6
     3225115.962    13794490.669      3222952.88    13793436.658
     3222758.373    13793320.693     3222649.865     13793251.14
     3222449.472    13793122.028     3220388.644    13792036.554
#Sta/Elev= 30
 2303.45   11.16 2812.82    9.59 3771.29    9.28 4041.55    15.2 4363.03   16.16
 4678.86   10.35 4935.61    9.21 4963.05     .07 4999.83   -1.58 5031.92     .02
 5064.39    8.23 5175.14     9.4 5242.32   15.23 5303.51    9.24 5342.39     9.3
 5436.77   11.29 5474.47    8.03 5923.52    9.32    5992    7.54 6025.31   12.85
 6058.62    7.87 6143.23    9.32 6713.79    9.85 6761.48   12.81 6800.39    9.37
 7356.88    9.39 7519.68    6.97 7551.28   11.93 7602.16   12.66 7632.61    9.71
#Mann= 7 ,-1 , 0
 2303.45     .15       0 2812.82     .12       0 4678.86     .07       0
 4935.61    .035       0 5064.39     .07       0 5342.39     .15       0
 6143.23     .12       0
#XS Ineff= 2 , 0
       0    4887    10.5    6030       0    12.2
Permanent Ineff=
       F       F
#Block Obstruct= 2 ,-1
 7599.86 7666.51   12.62    5252    6018      12
Bank Sta=4935.61,5064.39
XS Rating Curve= 0
Exp/Cntr=.5,.3

Type RM Length L Ch R = 3 ,6124    ,,,
BEGIN DESCRIPTION:
12" pipe crossing
END DESCRIPTION:
Bridge Culvert--1,0,-1,-1, 0
Deck Dist Width WeirC Skew NumUp NumDn MinLoCord MaxHiCord MaxSubmerge Is_Ogee
1,1,2.6,0, 6, 6, , , .95, 0, 0,0,,
    4915    4917    4917    5078    5078    5080
   15.18   15.18   15.18   15.18   15.18   15.18
                   11.81   11.81
    4915    4917    4917    5088    5088    5090
   15.18   15.18   15.18   15.18   15.18   15.18
                   11.81   11.81
Pier Skew, UpSta & Num, DnSta & Num=  ,4965, 4 ,4965, 4 , 3 , 3 , 0 ,,
       1       1       2       2
      -2    9.81    9.82      12
       1       1       2       2
      -2    9.81    9.82      12
Pier Skew, UpSta & Num, DnSta & Num=  ,5020, 4 ,5020, 4 , 3 , 3 , 0 ,,
       1       1       2       2
      -2    9.81    9.82      12
       1       1       2       2
      -2    9.81    9.82      12
BR Coef=-1 , 1 , 0 ,, 0 ,,,.8,-1,2,0,
WSPro=,,,, 1 ,,,, 0 ,,,, 0 ,,,,-1 ,-1 ,-1 , 0 , 0 , 0 , 0 , 0
BC Design=,, 0 ,, 0 ,,,,,,

Type RM Length L Ch R = 1 ,6123.113,950.1,939.7,913.56
XS GIS Cut Line= 6
     3225116.838    13794488.871     3222953.832    13793434.897
     3222759.425    13793318.992     3222650.946    13793249.457
     3222450.481    13793120.299     3220389.576    13792034.785
#Sta/Elev= 30
 2303.48   11.13 2825.62    9.49  3768.8    9.28 4041.56   15.27 4097.45   13.68
 4364.48   16.21 4709.61   10.35 4935.61    9.21 4963.05     .07 4999.83   -1.58
 5031.92     .02 5064.39    8.23 5174.06    9.31 5242.08   15.22 5302.87     8.9
 5336.17    8.66 5436.12   11.31 5473.01    7.69 5991.34    7.28 6024.66   12.85
 6057.97     7.6 6123.27    8.75 6713.14    9.45 6761.49   12.82 6784.46     9.6
 6867.42    8.77 7519.69    6.87 7551.57   11.94  7601.5   12.66 7632.57     9.5
#Mann= 7 ,-1 , 0
 2303.48     .15       0 2825.62     .12       0 4709.61     .07       0
 4935.61    .035       0 5064.39     .07       0 5336.17     .15       0
 6123.27     .12       0
#XS Ineff= 2 , 0
       0    4887    10.5    6030       0    12.2
Permanent Ineff=
       F       F
#Block Obstruct= 2 ,-1
 7599.86 7666.51   12.62    5252    6018      12
Bank Sta=4935.61,5064.39
XS Rating Curve= 0
Exp/Cntr=.5,.3

Type RM Length L Ch R = 1 ,5183.417,491.26,268.48,84.22
XS GIS Cut Line= 4
     3225154.891    13793583.636     3223256.491     13792514.93
     3223010.246    13792381.254      3220793.41    13791306.468
#Sta/Elev= 30
 2684.03   11.48 2684.03   10.48 2747.06    7.49 2937.28   11.62 3157.51    7.64
 3263.47   10.47  3637.7    8.96 3698.88      11 3898.39    5.18 3925.26    8.62
 4573.83    8.56 4818.67   10.49 4933.14    7.37 4960.95    -.17 5011.25   -2.46
 5035.73     .29 5056.86    7.78 5125.35    7.95 5245.05   14.47 5335.53   10.04
 5477.97   12.24 5983.19    8.23  6015.2    10.1 6059.82     7.7 6083.91   10.85
 6141.64   11.03 6873.13    9.85 7522.57    7.57 7542.45   10.75  7606.4   11.19
#Mann= 6 ,-1 , 0
 2684.03     .15       0 3925.26     .12       0 4573.83     .07       0
 4933.14    .035       0 5056.86     .15       0 6873.13     .07       0
#XS Ineff= 2 ,-1
    2680    4811    10.1    5910    7555    10.1
Permanent Ineff=
       F       F
Bank Sta=4933.14,5056.86
XS Rating Curve= 0
Exp/Cntr=.3,.1

Type RM Length L Ch R = 1 ,4914.941,11.42,12.93,10.07
XS GIS Cut Line= 6
     3225180.186    13793362.874     3224020.008    13792220.232
     3223827.278    13792149.737     3223579.593    13792157.819
     3222986.729    13792278.733      3220862.65    13791155.582
#Sta/Elev= 30
 2588.04   11.07 2588.04   10.07 2659.09    10.1 2701.54    6.82 2890.25   10.22
 3410.06   10.06 3452.55    5.94 3566.62   10.77 3997.32    8.59 4058.08    3.99
 4137.97    7.56 4374.72    8.34 4756.25   11.49    4900    9.08 5003.36   -2.01
 5040.52    -.39 5068.74    8.62 5317.61   14.39 5360.97   11.11 5747.85    8.93
 5976.77   11.48 6055.78    7.67 6089.34   10.18  6129.6    7.72 6173.61   10.21
 6478.54    8.48 6777.58   11.45  7585.6    7.31  7615.4   10.79 7681.95   10.25
#Mann= 6 ,-1 , 0
 2588.04     .15       0 3997.32     .07       0 4374.72     .15       0
    4900    .035       0 5068.74     .15       0 5976.77     .07       0
#XS Ineff= 2 , 0
       0    4700    10.5    5300       0    10.5
Permanent Ineff=
       F       F
#Block Obstruct= 1 ,-1
  7659.9 7705.39   11.42
Bank Sta=4900,5068.74
XS Rating Curve= 0
Exp/Cntr=.5,.3

Type RM Length L Ch R = 1 ,4902.016,41.83,43.69,34.17
XS GIS Cut Line= 6
     3225189.856    13793198.495     3224020.954    13792203.882
     3223828.414    13792139.703     3223578.545    13792147.851
     3222989.139    13792268.684     3220871.736     13791134.38
#Sta/Elev= 30
 2686.76   11.31 2686.76   10.31 2745.94   10.28 2785.48    6.26 3089.91   10.27
 3832.69   10.58 3992.91    7.94 4377.96    8.52 4755.95   11.71 4906.85    9.07
 4930.16    6.44 4932.54    -.41 4994.68   -1.93 5035.19     .02 5093.15    9.39
 5316.96   14.39  5358.5   11.21 5749.59    8.75 5988.23   11.18 6055.16    7.67
 6088.71   10.19 6128.98    7.71 6176.06   10.07 6477.94    8.39 6768.35   11.43
 7204.57    9.53 7235.41    7.04 7585.24    7.21 7618.26   10.97 7682.96   11.14
#Mann= 6 ,-1 , 0
 2686.76     .15       0 3992.91     .07       0 4377.96     .15       0
 4906.85    .035       0 5093.15     .15       0 5988.23     .07       0
#XS Ineff= 2 , 0
       0    4750    10.5    5200       0    10.5
Permanent Ineff=
       F       F
#Block Obstruct= 1 ,-1
    7625    7690   11.03
Bank Sta=4906.85,5093.15
XS Rating Curve= 0
Exp/Cntr=.5,.3

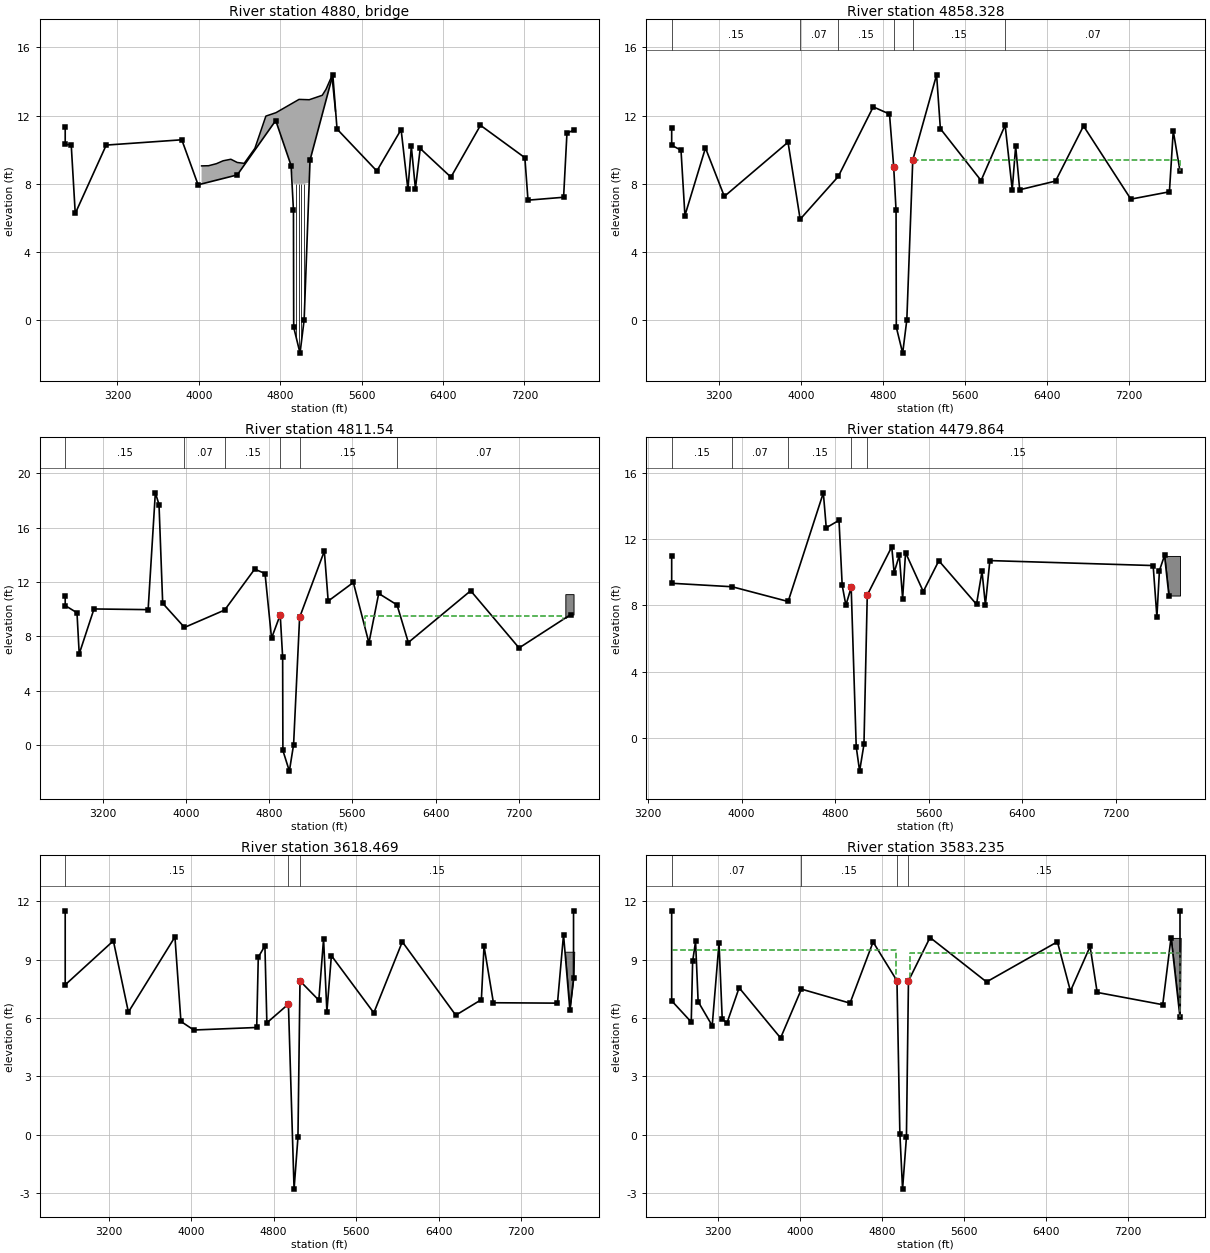
Type RM Length L Ch R = 3 ,4880    ,,,
BEGIN DESCRIPTION:
RR Bridge
END DESCRIPTION:
Bridge Culvert--1,0,-1,-1, 0
Deck Dist Width WeirC Skew NumUp NumDn MinLoCord MaxHiCord MaxSubmerge Is_Ogee
10,32,2.6,0, 16, 16, , , .95, 0, 0,0,,
    4027    4096    4173    4239    4315    4378    4446    4551    4659    4758
    4985    5085    5213    5250    5308    5343
    9.05    9.06    9.18    9.35    9.44    9.25     9.2   10.08   11.97   12.17
   12.95   12.93   13.19   13.54   14.33   12.27
                                                                               8
       8       8
    4027    4096    4173    4239    4315    4378    4446    4551    4659    4758
    4985    5085    5213    5250    5308    5343
    9.05    9.06    9.18    9.35    9.44    9.25     9.2   10.08   11.97   12.17
   12.95   12.93   13.19   13.54   14.33   12.27
                                                                               8
       8       8
Pier Skew, UpSta & Num, DnSta & Num=  ,4956, 4 ,4956, 4 , 3 , 3 , 0 ,,
     1.5     1.5       2       2
      -2     5.9       6       8
     1.5     1.5       2       2
      -2     5.9       6       8
Pier Skew, UpSta & Num, DnSta & Num=  ,4982, 4 ,4982, 4 , 3 , 3 , 0 ,,
     1.5     1.5       2       2
      -2     5.9       6       8
     1.5     1.5       2       2
      -2     5.9       6       8
Pier Skew, UpSta & Num, DnSta & Num=  ,5008, 4 ,5008, 4 , 3 , 3 , 0 ,,
     1.5     1.5       2       2
      -2     5.9       6       8
     1.5     1.5       2       2
      -2     5.9       6       8
Pier Skew, UpSta & Num, DnSta & Num=  ,5034, 4 ,5034, 4 , 3 , 3 , 0 ,,
     1.5     1.5       2       2
      -2     5.9       6       8
     1.5     1.5       2       2
      -2     5.9       6       8
BR Coef=-1 , 1 , 0 ,1.25, 0 ,,,.8,-1,2,0,
WSPro=,,,, 1 ,,,, 0 ,,,, 0 ,,,,-1 ,-1 ,-1 , 0 , 0 , 0 , 0 , 0
BC Design=,, 0 ,, 0 ,,,,,,

Type RM Length L Ch R = 1 ,4858.328,38.14,46.79,35.76
XS GIS Cut Line= 6
     3225216.446     13793084.88     3224047.049    13792180.443
      3223938.41    13792130.197     3223574.471    13792112.544
     3222998.686    13792234.762     3220877.794    13791101.063
#Sta/Elev= 30
 2740.32   11.26 2740.32   10.26 2831.39    9.97 2869.61    6.14 3070.02    10.1
 3254.37    7.26 3875.88   10.44 3994.15    5.92 4366.32    8.43 4707.37   12.51
    4866   12.09 4906.85    9.01 4930.16    6.44 4932.54    -.41 4994.68   -1.93
 5035.19     .02 5093.15    9.39 5325.76   14.39 5362.65   11.23 5759.91    8.19
 5994.79   11.44 6063.86    7.66 6097.41    10.2  6136.8    7.65  6486.6    8.16
 6759.58   11.39 7221.44     7.1  7597.9    7.53 7635.33    11.1 7701.21    8.75
#Mann= 6 ,-1 , 0
 2740.32     .15       0 3994.15     .07       0 4366.32     .15       0
 4906.85    .035       0 5093.15     .15       0 5994.79     .07       0
#XS Ineff= 2 , 0
       0 4906.85    9.01 5093.15       0    9.39
Permanent Ineff=
       F       F
Bank Sta=4906.85,5093.15
XS Rating Curve= 0
Exp/Cntr=.5,.3

Type RM Length L Ch R = 1 ,4811.54 ,120.25,331.67,554.33
XS GIS Cut Line= 6
     3225226.116    13792901.162       3223945.2    13792103.038
     3223835.203     13792074.52     3223571.209    13792078.075
     3223006.015     13792198.34     3220895.967    13791079.861
#Sta/Elev= 30
 2841.24      11 2841.24   10.26 2954.41    9.73  2975.8     6.7 3117.75   10.01
 3637.82    9.96 3707.07   18.56 3742.39    17.7 3777.71   10.43 3987.17    8.65
 4373.18    9.93 4661.13   12.94 4760.91   12.62 4823.49    7.86 4906.85    9.58
 4930.16    6.44 4932.54    -.41 4994.68   -1.93 5035.19     .02 5093.15    9.39
 5330.57   14.27 5367.55   10.59 5609.31   11.96 5758.92    7.51 5853.06   11.15
 6028.92   10.31 6137.53    7.54 6736.53   11.35 7201.31    7.14 7697.84     9.6
#Mann= 6 ,-1 , 0
 2841.24     .15       0 3987.17     .07       0 4373.18     .15       0
 4906.85    .035       0 5093.15     .15       0 6028.92     .07       0
#XS Ineff= 2 ,-1
    2924    4444     9.5    5720    7623     9.5
Permanent Ineff=
       F       F
#Block Obstruct= 1 ,-1
    7646 7724.62    11.1
Bank Sta=4906.85,5093.15
XS Rating Curve= 0
Exp/Cntr=.3,.1

Type RM Length L Ch R = 1 ,4479.864,873.22,861.4,853.4
XS GIS Cut Line= 6
     3224921.874    13792541.554     3223654.854    13791938.654
     3223545.455    13791873.839     3223426.161    13791805.071
     3223198.689    13791671.248     3221161.401    13790562.145
#Sta/Elev= 30
 3401.42      11 3401.42    9.33 3918.49    9.12 4397.25    8.23 4698.14   14.79
 4723.09   12.68 4832.13   13.13  4859.3    9.21 4890.94    8.01 4936.26    9.08
 4979.29    -.54 5008.36   -2.01 5045.52    -.39 5073.74    8.62 5283.13   11.53
 5303.28    9.98 5347.77   11.01 5376.12    8.41 5401.11   11.18  5552.7    8.83
 5685.66   10.69 6007.85    8.06 6054.89   10.05 6083.76    8.02 6121.96    10.7
 7518.11    10.4 7550.17     7.3 7571.81    10.1 7615.43   11.01 7652.96    8.59
#Mann= 5 ,-1 , 0
 3401.42     .15       0 3918.49     .07       0 4397.25     .15       0
 4936.26    .035       0 5073.74     .15       0
#Block Obstruct= 1 ,-1
 7616.41 7747.67   10.98
Bank Sta=4936.26,5073.74
XS Rating Curve= 0
Exp/Cntr=.3,.1

Type RM Length L Ch R = 1 ,3618.469,30.09,35.23,30
XS GIS Cut Line= 6
     3225106.919    13792747.019     3225009.909    13792107.949
      3224769.99    13791685.274     3224601.391    13791498.916
      3224269.19    13791265.408     3221488.848     13789822.74
#Sta/Elev= 30
 2780.22    11.5 2780.22     7.7 3247.12    9.96 3392.77     6.3 3843.89   10.16
 3901.88    5.82 4026.48    5.38 4636.44    5.51 4651.79    9.12 4715.96     9.7
 4735.05    5.75 4943.89    6.71 4998.59   -2.79 5036.27    -.13 5056.11     7.9
 5238.63    6.91  5284.6   10.06 5316.81    6.32 5360.38     9.2  5771.6    6.26
 6047.83    9.91 6566.04    6.14 6814.37    6.94 6839.86    9.69 6930.95    6.78
 7552.01    6.76  7610.6   10.28 7671.76    6.43  7707.6    8.03  7707.6    11.5
#Mann= 3 ,-1 , 0
 2780.22     .15       0 4943.89    .035       0 5056.11     .15       0
#Block Obstruct= 2 ,-1
                            7614    7725     9.4
Bank Sta=4943.89,5056.11
XS Rating Curve= 0
Exp/Cntr=.5,.3

Type RM Length L Ch R = 1 ,3583.235,120.37,125.7,120
XS GIS Cut Line= 6
     3225136.878    13792745.442     3225038.155    13792097.576
     3224794.549    13791667.982     3224621.243    13791476.379
     3224283.305    13791238.909     3221502.654    13789796.106
#Sta/Elev= 30
 2745.83    11.5 2745.83    6.88 2936.73    5.79 2950.19     8.9  2978.9    9.93
 3003.92    6.84  3141.3     5.6 3207.76    9.85 3238.92    5.96 3284.76    5.73
 3403.87    7.55 3808.51    4.97 4011.73    7.48 4485.95    6.76 4711.03     9.9
 4943.89    7.91 4972.27     .06 4998.59   -2.79 5036.27    -.13 5056.11     7.9
 5266.55   10.13 5817.81    7.85 6509.39    9.91 6636.62    7.38 6828.25    9.67
 6897.55    7.31 7536.99    6.68 7618.29   10.13 7705.51    6.03 7705.51    11.5
#Mann= 4 ,-1 , 0
 2745.83     .07       0 4011.73     .15       0 4943.89    .035       0
 5056.11     .15       0
#XS Ineff= 2 , 0
       0    4930    9.49    5070       0    9.33
Permanent Ineff=
       F       F
#Block Obstruct= 1 ,-1
 7620.35 7714.87   10.11
Bank Sta=4943.89,5056.11
XS Rating Curve= 0
Exp/Cntr=.5,.3

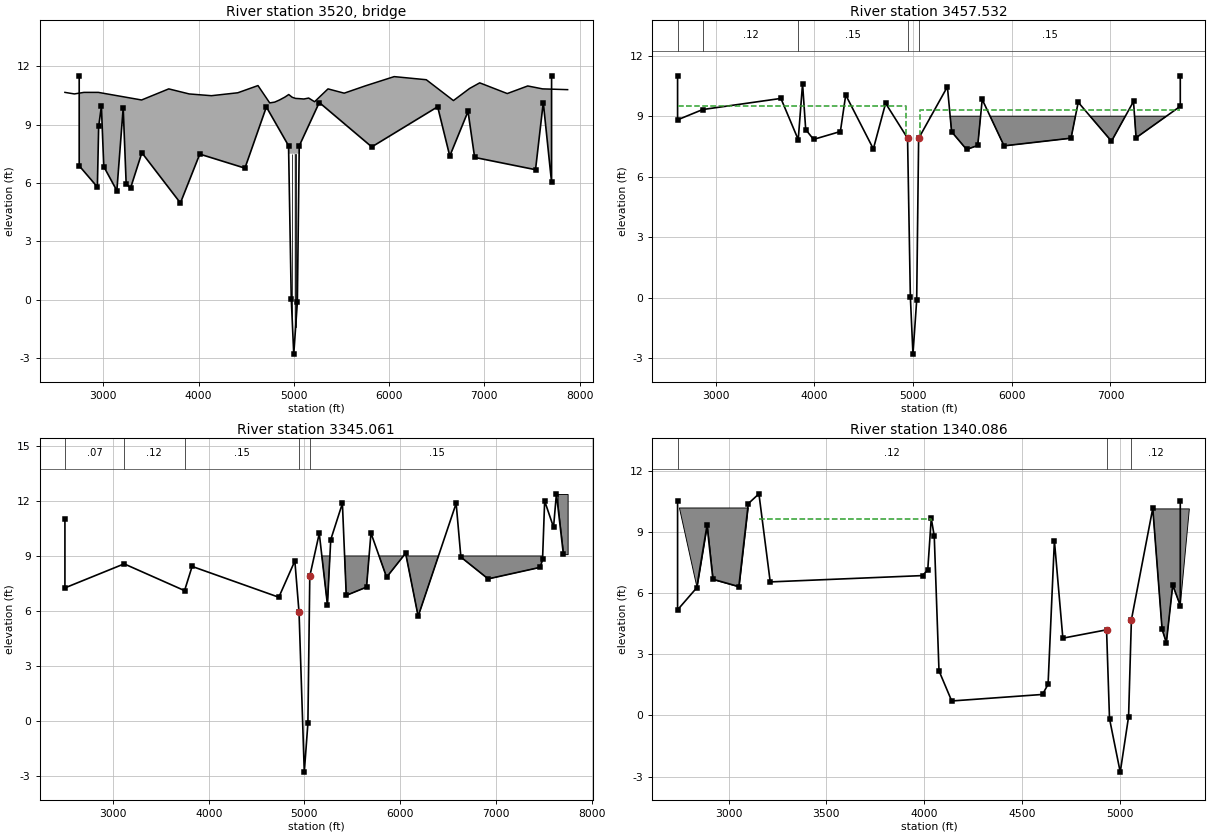
Type RM Length L Ch R = 3 ,3520    ,,,
BEGIN DESCRIPTION:
BAY AREA BLVD.
END DESCRIPTION:
Bridge Culvert--1,0,-1,-1, 0
Deck Dist Width WeirC Skew NumUp NumDn MinLoCord MaxHiCord MaxSubmerge Is_Ogee
17,101,2.6,0, 33, 32, , , .95, 0, 0,0,,
    2596    2695    2795    2947    3401    3686    3901    4134    4411    4623
    4746    4798    4849    4906    4946    4982    5018    5054    5105    5155
    5217    5358    5528    5753    6053    6390    6675    6844    6951    7240
    7455    7611    7874
   10.65   10.57   10.65   10.65   10.26   10.83   10.57   10.48   10.63      11
   10.11   10.15   10.26   10.41   10.54    10.4   10.34   10.33   10.31   10.36
   10.17   10.83   10.61   10.99   11.46    11.3   10.23   10.85   11.14   10.59
   10.98   10.83   10.79
                                                                                
     7.5     7.5     7.5     7.5     7.5     7.5     7.5     7.5     7.5     7.5
     7.5
                        
    2596    2695    2947    3401    3686    3901    4134    4411    4623    4746
    4798    4849    4906    4946    4982    5018    5054    5105    5155    5217
    5358    5528    5753    6053    6390    6675    6844    6951    7240    7455
    7611    7874
   10.65   10.52   10.65   10.26   10.83   10.57   10.48   10.63      11   10.11
   10.15   10.26   10.41   10.54    10.4   10.34   10.33   10.31   10.36   10.17
   10.83   10.61   10.99   11.46    11.3   10.23   10.85   11.14   10.59   10.98
   10.83   10.79
                                                                             7.5
     7.5     7.5     7.5     7.5     7.5     7.5     7.5     7.5     7.5     7.5
                                                                                
                
Pier Skew, UpSta & Num, DnSta & Num=  ,4981, 4 ,4981, 4 , 3 , 3 , 0 ,,
     1.5     1.5     2.4     2.4
      -3    5.49     5.5       8
     1.5     1.5     2.4     2.4
      -3    5.49     5.5       8
Pier Skew, UpSta & Num, DnSta & Num=  ,5018, 4 ,5018, 4 , 3 , 3 , 0 ,,
     1.5     1.5     2.4     2.4
      -3    5.49     5.5       8
     1.5     1.5     2.4     2.4
      -3    5.49     5.5       8
BR Coef=-1 , 1 , 0 ,, 0 ,,,.8,0,2,0,
WSPro=,,,, 1 ,,,, 0 ,,,, 0 ,,,,-1 ,-1 ,-1 , 0 , 0 , 0 , 0 , 0
BR U #Sta/Elev= 30
 2745.83    11.5 2745.83    6.88 2936.73    5.79 2950.19     8.9  2978.9    9.93
 3003.92    6.84  3141.3     5.6 3207.76    9.85 3238.92    5.96 3284.76    5.73
 3403.87    7.55 3808.51    4.97 4011.73    7.48 4485.95    6.76 4711.03     9.9
 4943.89    7.91 4972.27     .06 4998.59   -2.79 5036.27    -.13 5056.11     7.9
 5266.55   10.13 5817.81    7.85 6509.39    9.91 6636.62    7.38 6828.25    9.67
 6897.55    7.31 7536.99    6.68 7618.29   10.13 7705.51    6.03 7705.51    11.5
BR U #Mann= 4
 2745.83     .07 4011.73     .15 4943.89     .02 5056.11     .15
BR D #Sta/Elev= 30
 2613.67      11 2613.67    8.82 2868.35    9.33 3660.72    9.88 3836.12    7.84
 3879.99   10.61 3911.87    8.34 3991.22    7.85 4263.09    8.24 4317.31   10.05
 4597.33    7.38 4721.44    9.64 4943.89    7.91 4972.27     .06 4998.59   -2.79
 5036.27    -.13 5056.11     7.9 5347.65   10.46 5390.15    8.23 5542.08    7.35
 5655.17    7.55 5700.27    9.83 5921.72    7.53 6600.41    7.91 6672.94    9.69
 7010.13    7.76 7233.38    9.73 7259.26    7.93 7707.23    9.49 7707.23      11
BR D #Mann= 5
 2613.67     .07 2868.35     .12 3836.12     .15 4943.89     .02 5056.11     .15
BC Design=,, 0 ,, 0 ,,,,,,

Type RM Length L Ch R = 1 ,3457.532,120.37,112.47,120
XS GIS Cut Line= 6
     3225263.292    13792741.496     3225158.313    13792052.732
     3224899.706     13791594.41     3224700.651     13791386.23
     3224339.765    13791132.911     3221557.882     13789689.57
#Sta/Elev= 30
 2613.67      11 2613.67    8.82 2868.35    9.33 3660.72    9.88 3836.12    7.84
 3879.99   10.61 3911.87    8.34 3991.22    7.85 4263.09    8.24 4317.31   10.05
 4597.33    7.38 4721.44    9.64 4943.89    7.91 4972.27     .06 4998.59   -2.79
 5036.27    -.13 5056.11     7.9 5347.65   10.46 5390.15    8.23 5542.08    7.35
 5655.17    7.55 5700.27    9.83 5921.72    7.53 6600.41    7.91 6672.94    9.69
 7010.13    7.76 7233.38    9.73 7259.26    7.93 7707.23    9.49 7707.23      11
#Mann= 5 ,-1 , 0
 2613.67     .07       0 2868.35     .12       0 3836.12     .15       0
 4943.89    .035       0 5056.11     .15       0
#XS Ineff= 2 , 0
       0    4930    9.49    5070       0    9.33
Permanent Ineff=
       F       F
#Block Obstruct= 1 ,-1
    5173    7590       9
Bank Sta=4943.89,5056.11
XS Rating Curve= 0
Exp/Cntr=.5,.3

Type RM Length L Ch R = 1 ,3345.061,1856.19,2004.97,2143.71
XS GIS Cut Line= 6
     3225376.546    13792732.828     3225264.126    13792014.586
     3224991.026    13791529.645     3224780.059    13791296.081
     3224396.225    13791026.913     3221613.109    13789583.034
#Sta/Elev= 30
 2497.38      11 2497.38    7.26 3116.32    8.57 3747.39    7.11 3826.47    8.43
 4732.59    6.75    4900    8.73 4943.89    5.92 4998.59   -2.79 5036.27    -.13
 5056.11     7.9 5155.16   10.23 5240.45    6.34 5275.06    9.89 5396.92   11.87
 5437.19    6.85 5648.75     7.3 5695.43   10.25  5858.7    7.84 6057.48    9.15
 6188.56    5.71 6585.46   11.87 6634.89    8.94  6919.9    7.75 7464.52    8.38
 7488.31    8.81 7510.28      12 7603.19   10.57 7633.33   12.39 7705.75     9.1
#Mann= 5 ,-1 , 0
 2497.38     .07       0 3116.32     .12       0 3747.39     .15       0
 4943.89    .035       0 5056.11     .15       0
#Block Obstruct= 2 ,-1
 7646.01 7750.37   12.38    5170    7520       9
Bank Sta=4943.89,5056.11
XS Rating Curve= 0
Exp/Cntr=.3,.1

Type RM Length L Ch R = 1 ,1340.086,548.04,1340.09,581.13
XS GIS Cut Line= 4
     3226280.367    13790948.806     3225084.142    13789213.387
      3224902.03    13788952.717     3224827.043     13788831.31
#Sta/Elev= 30
 2739.78    10.5 2739.78    5.18  2837.4    6.26 2890.26    9.33 2920.19    6.68
 3052.74    6.32 3101.04   10.39  3155.4   10.87 3213.12    6.55 3991.14    6.86
 4017.99    7.14 4035.85    9.67 4051.17     8.8 4075.37    2.19  4140.4     .71
 4604.48    1.03 4632.71    1.53 4665.06    8.57  4708.2    3.79 4931.56     4.2
 4946.63    -.16 5001.44   -2.78 5044.06    -.06 5058.44    4.69 5167.66   10.16
 5215.23    4.23 5237.03    3.57 5269.73    6.39 5308.22    5.39 5308.22    10.5
#Mann= 3 ,-1 , 0
 2739.78     .12       0 4931.56    .035       0 5058.44     .12       0
#XS Ineff= 1 ,-1
    3155    4035    9.63
Permanent Ineff=
       F
#Block Obstruct= 2 ,-1
    2700    3102    10.2 5166.65 5358.17   10.13
Bank Sta=4931.56,5058.44
XS Rating Curve= 0
Exp/Cntr=.3,.1

Chan Stop Cuts=-1

--- A104_13_00.g01 (geometry) ---

Geom Title=A104-13-00 June 2007
Version=Version 3.0.1  Mar 2001

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
River Reach=A104-13-00,A104-13-00_0013

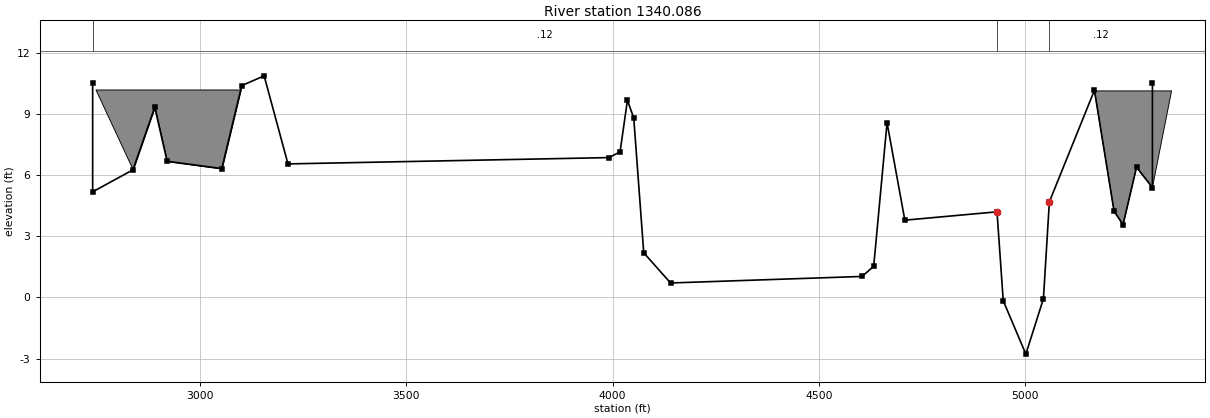
Type RM Length L Ch R = 1 ,1340.086,548.04,1340.09,581.13
XS GIS Cut Line= 4
     3226280.367    13790948.806     3225084.142    13789213.387
      3224902.03    13788952.717     3224827.043     13788831.31
#Sta/Elev= 30
 2739.78    10.5 2739.78    5.18  2837.4    6.26 2890.26    9.33 2920.19    6.68
 3052.74    6.32 3101.04   10.39  3155.4   10.87 3213.12    6.55 3991.14    6.86
 4017.99    7.14 4035.85    9.67 4051.17     8.8 4075.37    2.19  4140.4     .71
 4604.48    1.03 4632.71    1.53 4665.06    8.57  4708.2    3.79 4931.56     4.2
 4946.63    -.16 5001.44   -2.78 5044.06    -.06 5058.44    4.69 5167.66   10.16
 5215.23    4.23 5237.03    3.57 5269.73    6.39 5308.22    5.39 5308.22    10.5
#Mann= 3 ,-1 , 0
 2739.78     .12       0 4931.56    .035       0 5058.44     .12       0
#XS Ineff= 1 ,-1
    3155    4036     9.4
Permanent Ineff=
       F
#Block Obstruct= 2 ,-1
    2700    3102    10.2 5166.65 5358.17   10.13
Bank Sta=4931.56,5058.44
XS Rating Curve= 0
Exp/Cntr=.3,.1